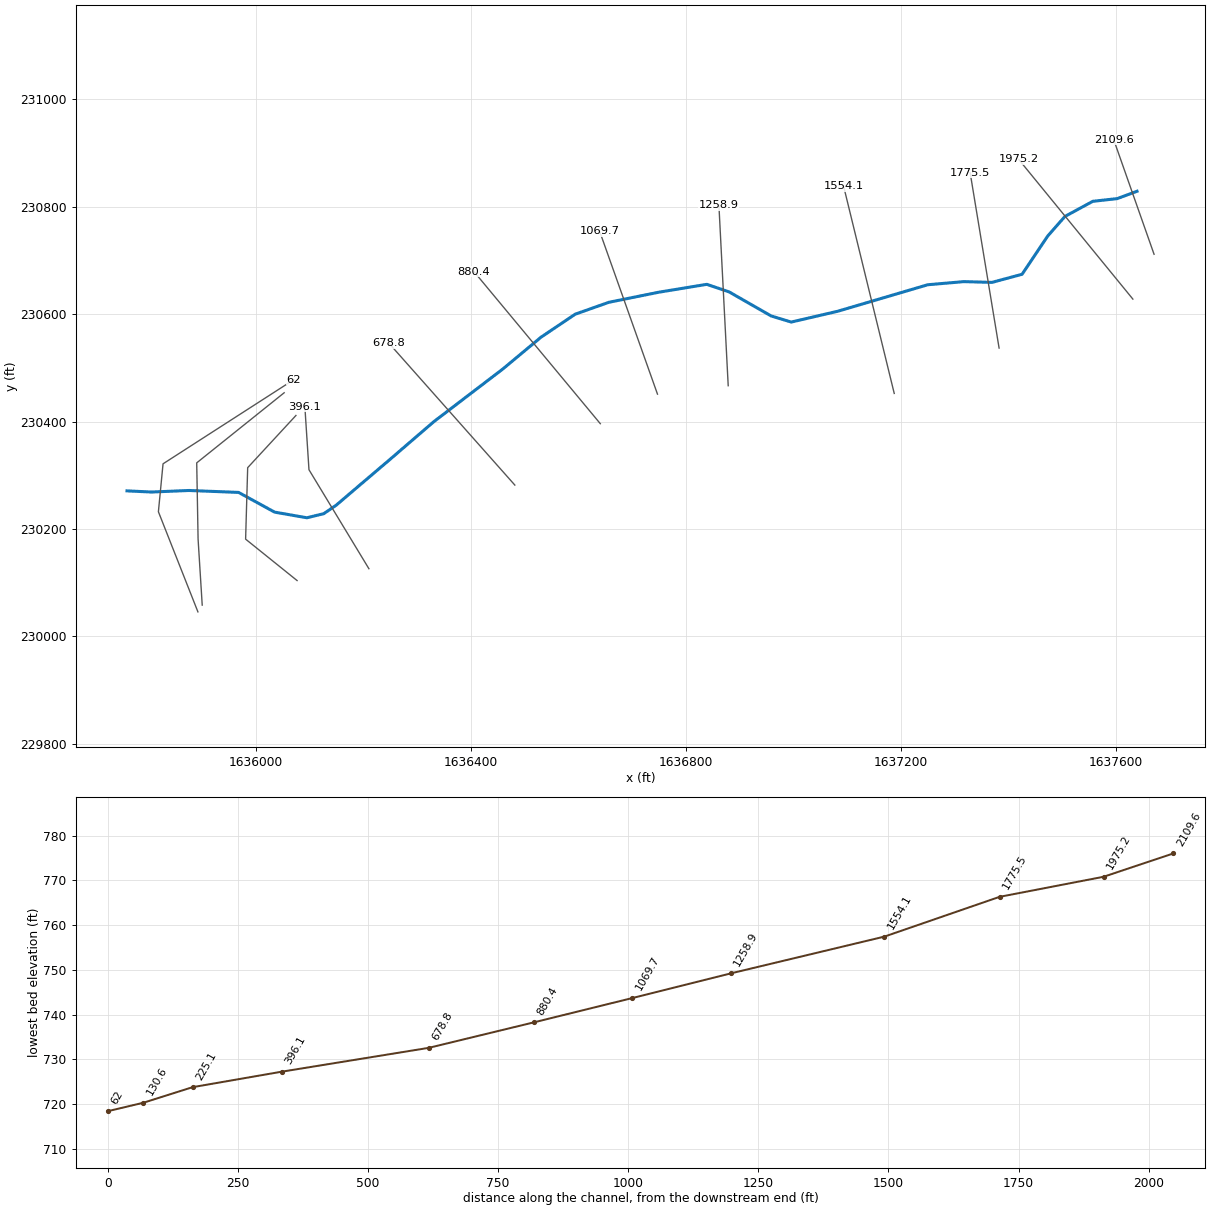
--- rthrfrdbrn.prj (project) ---

Proj Title=rthrfrdbrn
Current Plan=p01
Default Exp/Contr=0,0
English Units
Geom File=g01
Flow File=f01
Plan File=p01
BEGIN DESCRIPTION:
END DESCRIPTION:
DSS Export Rating Curves= 0
DSS Export Rating Curve Sorted= 0
DSS Export Volume Flow Curves= 0
DXF OffsetX= 0
DXF OffsetY= 0
DXF ScaleX= 0
DXF ScaleY= 0

--- rthrfrdbrn.p01 (plan) ---

Plan Title=Approximate Study  - 100yr
Program Version=4.00
Geom File=g01
Flow File=f01
Subcritical Flow
K Sum by GR= 0
Std Step Tol= 0.01
Critical Tol= 0.01
Num of Std Step Trials= 20
Max Error Tol= 0.3
Flow Tol Ratio= 0.001
Split Flow NTrial= 30
Split Flow Tol= 0.02
Split Flow Ratio= 0.02
Log Output Level= 0
Friction Slope Method= 1
Unsteady Friction Slope Method= 2
Unsteady Bridges Friction Slope Method= 1
Parabolic Critical Depth
Global Vel Dist= 0 , 0 , 0
Global Log Level= 0
CheckData=True
Encroach Param=-1 ,0,0, 0
Run HTab= 0
Run UNet= 0
Run PostProcess= 0
Run WQNet= 0
UNET Theta= 0
UNET Theta Warmup= 0
UNET ZTol= 0
UNET ZSATol= 0
UNET MxIter= 0
UNET MaxInSteps= 0
UNET DtIC= 0
UNET DtMin= 0
UNET MaxCRTS= 0
UNET WFStab= 0
UNET SFStab= 0
UNET WFX= 1
UNET SFX= 1
UNET DSS MLevel= 1
UNET DZMax Abort= 0
UNET Convert EG Bridges= 0
UNET Use Existing IB Tables= 0
UNET Froude Reduction=False
UNET Froude Limit= 0
UNET Froude Power= 0
UNET Time Slicing=0,0, 5
Write IC File= 0
Echo Input=False
Echo Output=False
Write Detailed= 0
Detailed Automatic Start=False, 0
WQ ULTIMATE=-1
WQ Max Comp Step=1HOUR
WQ Output Interval=15MIN
WQ Output Selected Increments= 0
WQ Output face flow=0
WQ Output face velocity=0
WQ Output face area=0
WQ Output face dispersion=0
WQ Output cell volume=0
WQ Output cell surface area=0
WQ Output cell continuity=0
WQ Output face conc=0
WQ Output face dconc_dx=0
WQ Output face courant=0
WQ Output face peclet=0
WQ Output face adv mass=0
WQ Output face disp mass=0
WQ Output cell mass=0
WQ Output cell source sink temp=0
WQ Output cell source sink nsm=0
WQ Output MaxMinRange=-1
WQ Daily Max Min Mean=-1
WQ Daily Range=0
WQ Daily Time=0
WQ Create Restart=0
WQ Fixed Restart=0
WQ System Summary=False
Sorting and Armoring Iterations= 10
XS Update Threshold= 0.02
Hydraulics Update Threshold= 0.02
Energy Slope Method= 1
Volume Change Method= 0
XS Weighting Method= 0
Number of US Weighted Cross Sections= 1
Number of DS Weighted Cross Sections= 1
Upstream XS Weight=0.25
Main XS Weight=0.5
Downstream XS Weight=0.25
Number of DS XS's Weighted with US Boundary= 1
Upstream Boundary Weight= 1
Weight of XSs Associated with US Boundary= 0
Number of US XS's Weighted with DS Boundary= 1
Downstream Boundary Weight= 0.5
Weight of XSs Associated with DS Boundary= 0.5
Sediment Output Level= 4
Mass or Volume Output= 0
Output Increment Type= 1
Profile and TS Output Increment= 10
XS Output Flag= 0
XS Output Increment= 10
Disregard all LS=0
Disregard all Conn=0
Disregard all Breaches=0
Disregard all Pumps=0

--- rthrfrdbrn.f01 (steady flow) ---

Flow Title=USGS Regression Equation
Program Version=4.00
Number of Profiles= 1
Profile Names=P100yr
River Rch & RM=rthrfrdbrn,Main            ,2109.6
     350
River Rch & RM=rthrfrdbrn,Main            ,225.1
     379
Boundary for River Rch & Prof#=rthrfrdbrn,Main            , 1
Up Type= 0
Dn Type= 3
Dn Slope=0.027256
DSS Import GetInterval= 0
DSS Import GetPeak= 0
DSS Import FillOption= 0

--- rthrfrdbrn.g01 (geometry) ---

Geom Title=USGS 3m DEM
Program Version=4.00

River Reach=rthrfrdbrn      ,Main
Reach XY= 29
     1637638.691      230829.009     1637601.956      230815.323
     1637556.576      230810.281     1637504.725      230782.123
     1637472.666      230745.585     1637424.982      230674.322
     1637369.009      230659.201     1637316.784      230660.639
     1637249.612      230654.814     1637081.834      230605.301
     1636995.794      230585.303     1636958.404      230596.692
      1636880.35      230641.488     1636838.768      230655.553
     1636749.834      230640.964     1636656.866      230622.151
     1636594.201      230599.973     1636530.699      230557.171
     1636459.367      230497.678     1636331.285      230399.696
     1636249.228      230328.922     1636149.662      230244.018
     1636126.696      230228.308     1636095.284      230220.639
     1636035.288      230231.154       1635968.3       230267.89
     1635876.101      230271.491     1635806.231       230268.61
     1635760.852      230270.771

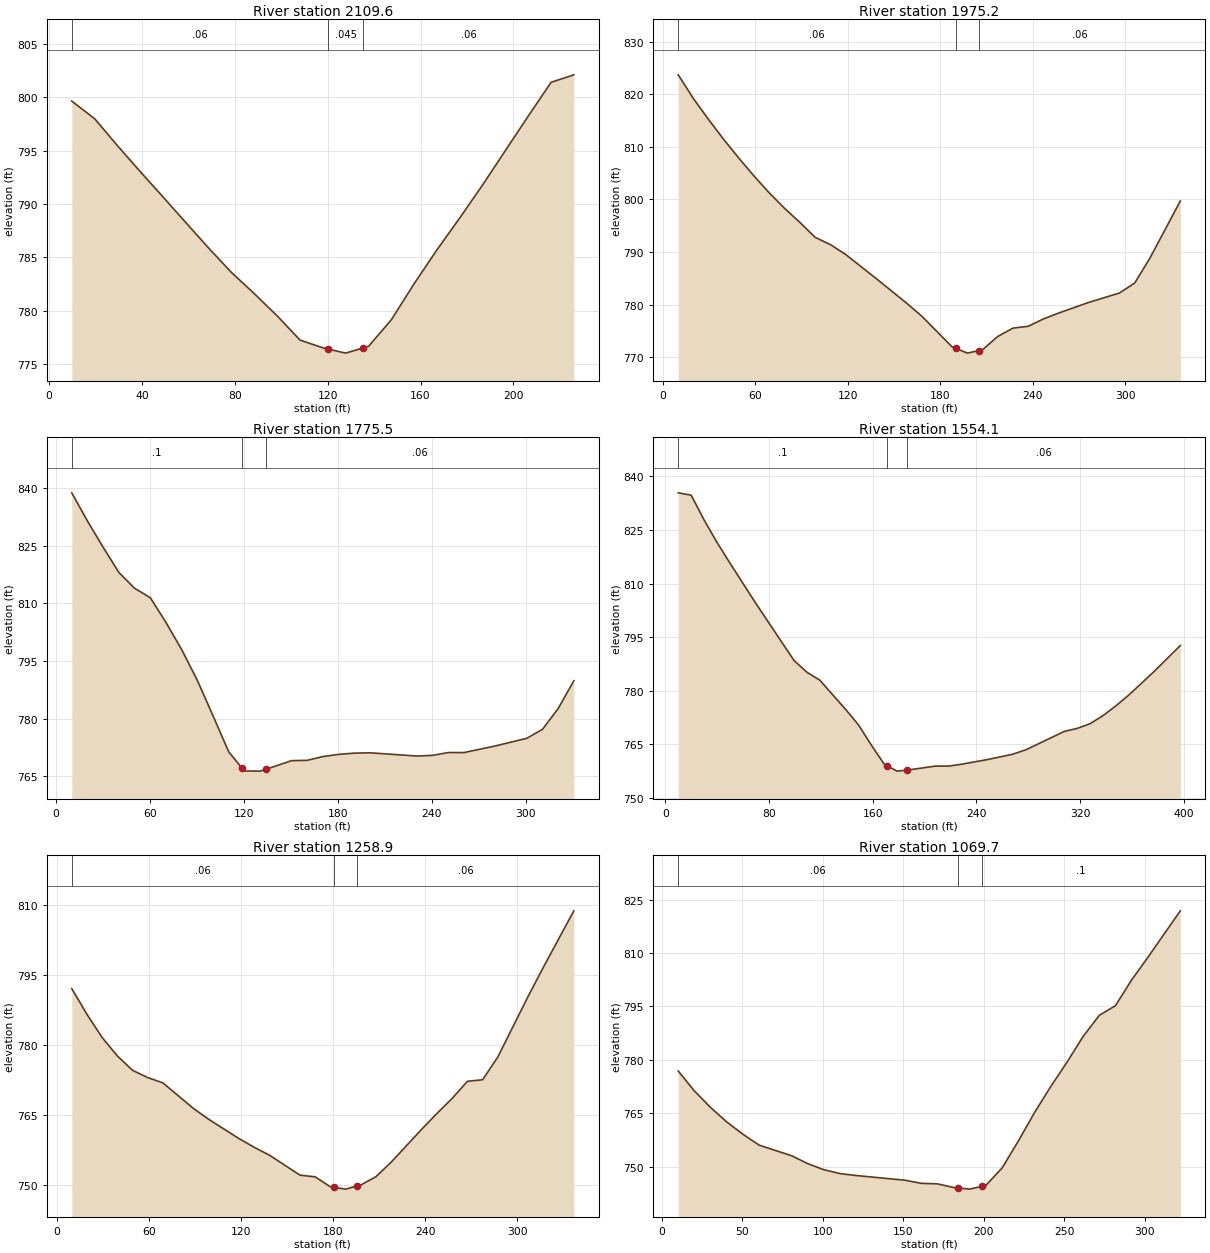
Type RM Length L Ch R = 1 ,2109.6  ,126.4,134.3,142.3
XS GIS Cut Line= 2
     1637670.385      230711.599     1637595.473      230924.809
#Sta/Elev= 25
     9.8  799.65    19.7  797.99    29.5  795.47    39.3  793.04    49.1  790.67
      59  788.25    68.8  785.87    78.6  783.59    88.4  781.61    98.3  779.52
   108.1  777.26   117.9  776.54   120.2  776.42   127.7  776.04   135.2  776.52
   137.6  776.68   147.4  779.16   157.2  782.53     167   785.7   176.9  788.71
   186.7  791.79   196.5  795.01   206.3  798.22   216.2  801.41     226  802.11
#Mann= 3 , 0 , 0
     9.8     .06       0   120.2    .045       0   135.2     .06       0
Bank Sta=120.2,135.2
XS Rating Curve= 0 ,0
Exp/Cntr=0.3,0.1

Type RM Length L Ch R = 1 ,1975.2  ,212.2,199.8,187.4
XS GIS Cut Line= 2
     1637631.008      230628.043     1637418.758      230888.314
#Sta/Elev= 30
     9.9  823.68    19.8  819.15    29.6  815.19    39.5  811.38    49.4   807.8
    59.3  804.39    69.1  801.22      79  798.29    88.9  795.64    98.8   792.8
   108.7  791.42   118.5  789.57   138.3     785     158  780.34   167.9  777.86
   187.7  771.99   190.1  771.71   197.6  770.81   205.1   771.3   207.4  771.45
   217.3  773.98   227.2  775.56   237.1  775.91   246.9   777.3   256.8  778.42
   276.6  780.47   296.3  782.23   306.2  784.13   316.1  788.87   335.8  799.71
#Mann= 3 , 0 , 0
     9.9     .06       0   190.1    .045       0   205.1     .06       0
Bank Sta=190.1,205.1
XS Rating Curve= 0 ,0
Exp/Cntr=0.3,0.1

Type RM Length L Ch R = 1 ,1775.5  ,219.7,221.4,223
XS GIS Cut Line= 2
     1637382.262      230536.804     1637328.479      230863.343
#Sta/Elev= 30
      10  838.75    20.1  831.36    30.1  824.56    40.1  818.03    50.1  813.92
    60.2  811.46    70.2  805.02    80.2  797.99    90.3  789.91   100.3  780.72
   110.3  771.35   118.9 767.059   120.3  766.36   130.4  766.32   133.9 766.763
   150.4  769.04   160.5  769.13   170.5  770.11   180.5  770.68   190.5     771
   200.6  771.09   230.7  770.24   240.7  770.43   250.7  771.16   260.7  771.15
   280.8  772.88   300.9  774.87   310.9  777.21   320.9  782.62   330.9  789.84
#Mann= 3 , 0 , 0
      10      .1       0   118.9    .045       0   133.9     .06       0
Bank Sta=118.9,133.9
XS Rating Curve= 0 ,0
Exp/Cntr=0.3,0.1

Type RM Length L Ch R = 1 ,1554.1  ,299.3,295.2,291.2
XS GIS Cut Line= 2
     1637187.299      230452.288     1637093.179      230838.373
#Sta/Elev= 30
     9.9  835.42    19.9  834.77    29.8  827.85    39.7   821.6    49.7  815.79
    69.5   804.6    99.3  788.41   109.3  785.12   119.2  782.91   139.1  774.72
     149  770.39     159  764.69   168.9  759.34   171.3  758.87   178.8  757.42
   186.3  757.69   208.6  758.84   218.6  758.83   228.5  759.35   248.4  760.65
   268.2  762.17   278.2   763.4     308  768.57   317.9   769.4   327.8  770.72
   337.8  772.99   347.7  775.72   357.7  778.76   377.5  785.46   397.4  792.62
#Mann= 3 , 0 , 0
     9.9      .1       0   171.3    .045       0   186.3     .06       0
Bank Sta=171.3,186.3
XS Rating Curve= 0 ,0
Exp/Cntr=0.3,0.1

Type RM Length L Ch R = 1 ,1258.9  ,182.9,189.2,195.5
XS GIS Cut Line= 2
     1636878.608      230466.694      1636861.32      230803.078
#Sta/Elev= 30
     9.9  792.05    19.8  786.55    29.7  781.59    39.6  777.65    49.5  774.58
    59.4  773.03    69.3  771.89    89.2  766.41    99.1  764.11   118.9  759.97
   128.8  758.11   138.7  756.43   158.5  752.18   168.4  751.81   178.3  749.69
   180.7  749.57   188.2  749.19   195.7  749.86   198.1  750.07     208  751.86
   217.9  754.97   237.8  762.01   247.7  765.38   257.6  768.59   267.5  772.24
   277.4  772.57   287.3  777.43   307.1  790.44     317  796.64   336.8  808.68
#Mann= 3 , 0 , 0
     9.9     .06       0   180.7    .045       0   195.7     .06       0
Bank Sta=180.7,195.7
XS Rating Curve= 0 ,0
Exp/Cntr=0.3,0.1

Type RM Length L Ch R = 1 ,1069.7  ,181.4,189.3,197.3
XS GIS Cut Line= 2
     1636747.112      230451.008     1636639.546      230754.497
#Sta/Elev= 30
    10.1  776.86    20.1  771.28    30.2  766.61    40.2  762.56    50.3  759.08
    60.4  756.02    80.5  753.06    90.6  750.82   100.6  749.12   110.7  748.03
   120.7  747.49   150.9  746.18     161   745.3   171.1  745.15   181.1  744.14
   183.7  744.02   191.2  743.67   198.7  744.46   201.2  744.72   211.3  749.62
   221.4  757.19   231.4  765.15   241.5  772.49   251.6  779.34   261.6  786.55
   271.7  792.52   281.7  795.21   291.8  802.48   301.9  808.83     322  821.87
#Mann= 3 , 0 , 0
    10.1     .06       0   183.7    .045       0   198.7      .1       0
Bank Sta=183.7,198.7
XS Rating Curve= 0 ,0
Exp/Cntr=0.3,0.1

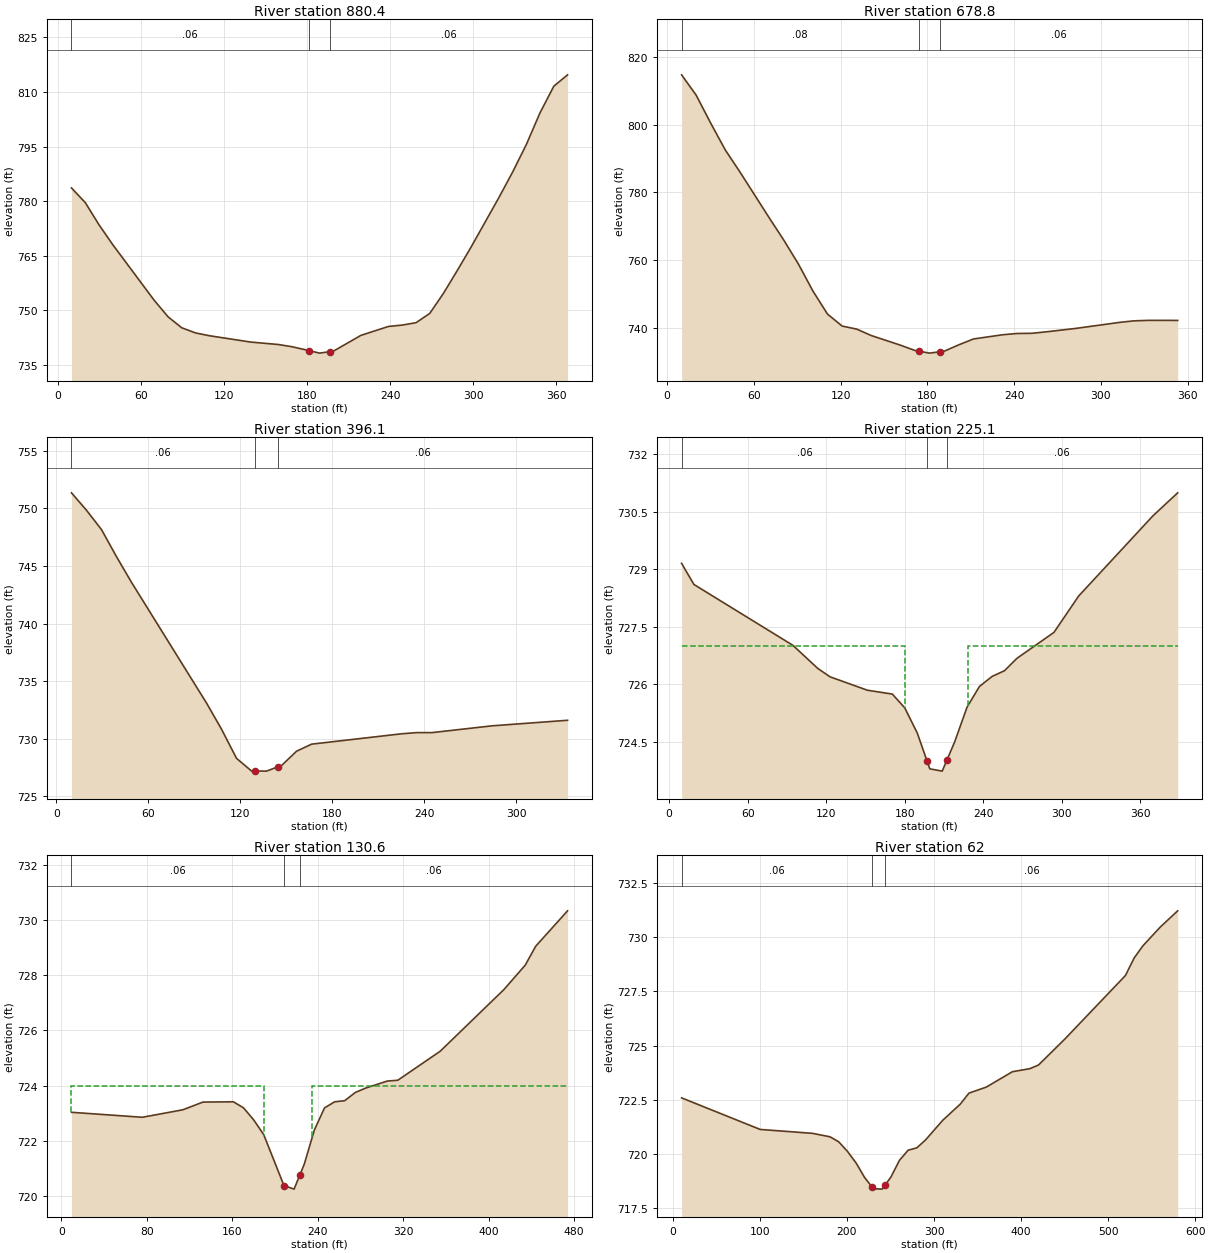
Type RM Length L Ch R = 1 ,880.4   ,200.8,201.5,202.3
XS GIS Cut Line= 2
     1636640.826      230395.944     1636405.906      230679.336
#Sta/Elev= 30
     9.9  783.63    19.9  779.58    29.8  773.49    39.8  767.99    69.6  752.77
    79.6  748.23    89.5   745.2    99.5  743.78   109.4  743.02   139.3  741.27
   159.2   740.6   169.1  739.99   181.5  738.92     189  738.23   196.5  738.63
     199  738.76   218.9  743.11   238.8  745.56   248.7  745.94   258.7  746.59
   268.6  749.14   278.6  754.72   288.5  760.95   298.5  767.41   318.4  780.89
   328.3  787.88   338.3  795.52   348.2  804.25   358.2  811.59   368.1  814.71
#Mann= 3 , 0 , 0
     9.9     .06       0   181.5    .045       0   196.5     .06       0
Bank Sta=181.5,196.5
XS Rating Curve= 0 ,0
Exp/Cntr=0.3,0.1

Type RM Length L Ch R = 1 ,678.8   ,286.9,282.8,278.7
XS GIS Cut Line= 2
     1636481.879      230281.576     1636247.779      230545.928
#Sta/Elev= 30
    10.1  814.72    20.2   808.7    30.3  800.39    40.4  792.47    50.4  786.06
    70.6  772.55    80.7  765.95    90.8   758.9   100.9  750.87     111  744.06
   121.1  740.53   131.2  739.63   141.2  737.74   161.4  734.89   171.5  733.31
   174.1  733.11   181.6  732.54   189.1  732.97   191.7  733.11   201.8     735
   211.9  736.72     232  737.96   242.1  738.34   252.2  738.39   262.3  738.83
   282.5  739.83   312.8  741.61   322.8  742.07   332.9  742.22   353.1   742.2
#Mann= 3 , 0 , 0
    10.1     .08       0   174.1    .045       0   189.1     .06       0
Bank Sta=174.1,189.1
XS Rating Curve= 0 ,0
Exp/Cntr=0.3,0.1

Type RM Length L Ch R = 1 ,396.1   ,183.3,171,158.7
XS GIS Cut Line= 3
     1636210.563      230125.749     1636099.156      230310.148
     1636091.472      230427.958
#Sta/Elev= 20
     9.8  751.34    19.6  749.83    29.4  748.15    39.2   745.8      49  743.57
    97.9  733.11   107.7  730.84   117.5  728.31   127.3  727.21   129.6  727.21
   137.1   727.2   144.6  727.58   146.9  727.69   156.7  728.93   166.5  729.54
   225.3  730.44   235.1  730.54     245  730.54   284.3  731.13   333.5  731.61
#Mann= 3 , 0 , 0
     9.8     .06       0   129.6    .045       0   144.6     .06       0
Bank Sta=129.6,144.6
XS Rating Curve= 0 ,0
Exp/Cntr=0.3,0.1

Type RM Length L Ch R = 1 ,225.1   ,94.1,94.5,94.8
XS GIS Cut Line= 4
     1636077.066       230103.66     1635981.345      230180.813
     1635985.187      230313.989     1636074.905      230411.231
#Sta/Elev= 23
     9.5  729.16    18.9  728.61    94.6  727.02   113.5  726.42   122.9   726.2
   151.5  725.85   170.5  725.75     180  725.39   189.6  724.73   197.1 723.996
   199.1   723.8   208.6  723.74   212.1  724.02   218.1   724.5   227.6  725.41
   237.1  725.95   246.7  726.21   256.2  726.36   265.6  726.68     294  727.36
   312.9  728.31   369.6   730.4   388.5     731
#Mann= 3 , 0 , 0
     9.5     .06       0   197.1    .045       0   212.1     .06       0
#XS Ineff= 2 , 0
       0     180     727     228       0     727
Permanent Ineff=
       F       F
Bank Sta=197.1,212.1
XS Rating Curve= 0 ,0
Exp/Cntr=0.3,0.1

Type RM Length L Ch R = 1 ,130.6   ,71.2,68.6,66
XS GIS Cut Line= 4
     1635900.671       230057.88     1635892.988      230180.813
     1635890.427      230322.953     1636053.056      230453.569
#Sta/Elev= 25
     9.5  723.04    75.8  722.86   113.7  723.13   132.6  723.41   161.1  723.42
   170.6   723.2     180  722.77   189.5  722.23   208.4  720.39   217.9  720.26
   223.4 720.781   227.4  721.16   236.9   722.4   246.4   723.2   255.9  723.42
   265.3  723.46   275.3  723.76   285.2  723.92   305.1  724.17     315   724.2
   354.7  725.25   414.3  727.48   434.2  728.36   444.1  729.05   473.9  730.33
#Mann= 3 , 0 , 0
     9.5     .06       0   208.4    .045       0   223.4     .06       0
#XS Ineff= 2 , 0
       0     190     724     235       0     724
Permanent Ineff=
       F       F
Bank Sta=208.4,223.4
XS Rating Curve= 0 ,0
Exp/Cntr=0.3,0.1

Type RM Length L Ch R = 1 ,62      ,60.9,62,63.1
XS GIS Cut Line= 4
     1635892.668      230045.315     1635819.196      230231.874
      1635827.84      230321.192     1636071.304      230478.219
#Sta/Elev= 30
      10  722.58   100.3  721.12   160.4  720.94   180.5  720.78   190.5  720.55
   200.5  720.11   210.5  719.57   220.4  718.89   228.9 718.457   230.4  718.38
   240.4  718.36   243.9 718.556   250.4  718.91   260.3  719.69   270.3  720.16
   280.3  720.27   290.2  720.63   310.2  721.55   330.2  722.29   340.2   722.8
   360.2  723.08   390.1  723.79   410.1  723.93   420.1   724.1   450.1  725.29
     520  728.24     530  729.05     540  729.61     560  730.48     580  731.23
#Mann= 3 , 0 , 0
      10     .06       0   228.9    .045       0   243.9     .06       0
Bank Sta=228.9,243.9
XS Rating Curve= 0 ,0
Exp/Cntr=0.3,0.1

Chan Stop Cuts=-1
Use User Specified Reach Order=0